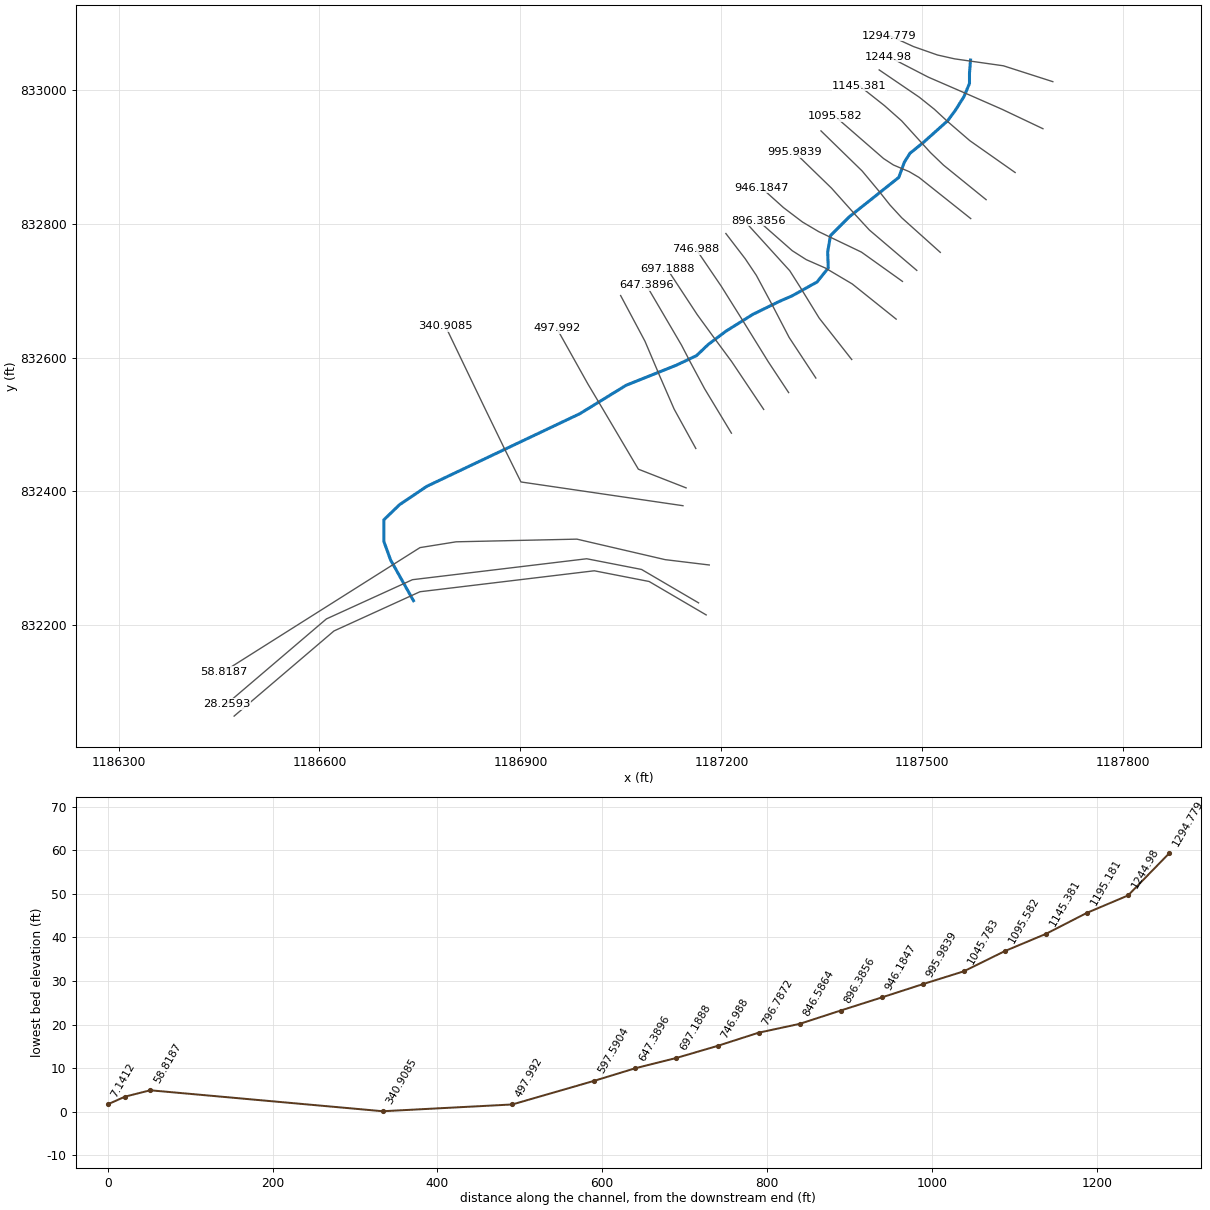
--- 14_ras.prj (project) ---

Proj Title=14
Current Plan=p01
Default Exp/Contr=0.3,0.1
English Units
Geom File=g01
Flow File=f01
Plan File=p01
Y Axis Title=Elevation
X Axis Title(PF)=Main Channel Distance
X Axis Title(XS)=Station
BEGIN DESCRIPTION:
RFD model 14 exported to HEC-RAS
END DESCRIPTION:

--- 14_ras.p01 (plan) ---

Plan Title=Plan 01
Program Version=4.10
Short Identifier=Plan 01
Geom File=g01
Flow File=f01
Subcritical Flow
Calc Critical at every XS
Secant Critical Depth

--- 14_ras.f01 (steady flow) ---

Flow Title=Flow 01
Program Version=5.01
Number of Profiles= 5
Profile Names=10yr,25yr,50yr,100yr,500yr
River Rch & RM=14,20,1294.779
   94.28  166.69  235.78  317.66  554.09
River Rch & RM=14,20, 58.8187
  103.05  182.56  258.69  349.24  612.47
River Rch & RM=14,20, 28.2593
  108.68  192.75  273.44  369.59  650.26
Boundary for River Rch & Prof#=14,20,1
Up Type= 0
Dn Type= 2
Boundary for River Rch & Prof#=14,20,2
Up Type= 0
Dn Type= 2
Boundary for River Rch & Prof#=14,20,2
Up Type= 0
Dn Type= 2
Boundary for River Rch & Prof#=14,20,2
Up Type= 0
Dn Type= 2
Boundary for River Rch & Prof#=14,20,2
Up Type= 0
Dn Type= 2

--- 14_ras.g01 (geometry) ---

Geom Title=14
Program Version=4.10

River Reach=14,20
Reach XY= 30
1187571.86823275833044.0447178251187570.33450809833024.413049416
1187570.33450764833009.0758084411187562.05239693832989.444140245
 1187549.1691139832968.8922377391187537.81955512832953.554997061
1187502.23715508832921.6535369031187481.37850683832904.782572448
1187473.09639632832891.5925454321187464.81428552832868.893429032
1187391.14515731832810.2625709981187362.81183149832781.929246874
1187358.64516534832757.7625874721187359.47849774832733.595927921
1187342.81183535832712.7626012131187305.31184576832691.929275138
1187286.14518448832683.5959448371187246.97852877832664.429284918
1187206.97853979832639.4292934881187180.31188038832619.429300175
1187162.81188504832602.7626389151187132.81189343832588.595977289
 1187057.8119146832558.5959883461186988.64526701832516.096002893
1186760.31199761832407.7627081731186719.47867546 832380.26271748
1186696.14534833832357.762724811 1186696.1453474832325.262734402
1186706.14534366832297.7627422321186740.31199853832236.929425905

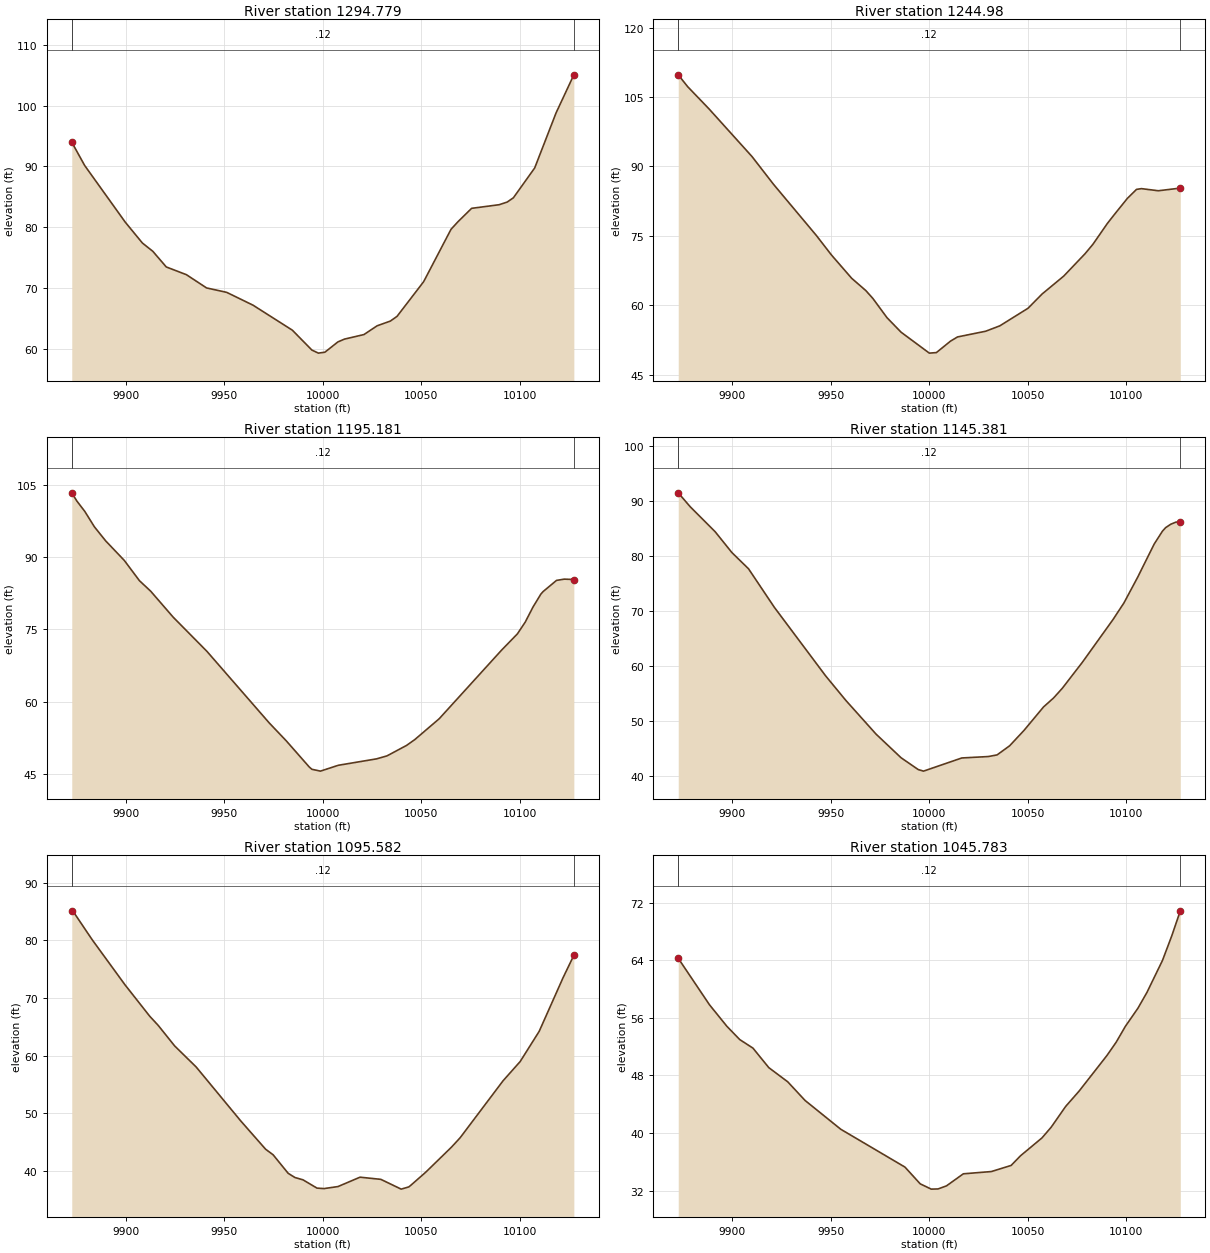
Type RM Length L Ch R = 1 ,1294.779,49.799200,49.799200,49.799200
XS GIS Cut Line= 6
1187694.76131103833011.7942644151187620.93889822833035.490516657
1187548.08765954833045.8549676041187522.58025303833051.605319348
1187486.90146656833064.1358380471187450.97656462833080.538228829
#Sta/Elev= 30
9872.656 93.99639879.20890.154989899.82780.820349908.49277.401459913.76176.04723
9920.58373.473599930.80672.198719941.02970.019959951.23269.290769964.58967.18356
9984.55163.065739994.45259.798569997.75359.2954210001.0559.4501910007.6661.14286
10010.9661.5988110020.8762.3505610027.5563.7930510034.27 64.570210037.64 65.3439
10051.1371.0435610065.03 79.667510068.5180.8967910075.4783.1113410089.4383.70829
 10093.584.1412610096.6584.8456310107.4789.7584110118.2998.8001510127.32 105.073
#Mann= 3 , 0 , 0
9872.656    0.12       09872.656    0.12       010127.32    0.12       0
#XS Ineff= 2 , 0
       0                               0
Bank Sta=9872.656,10127.32
Exp/Cntr=0.3,0.1

Type RM Length L Ch R = 1 , 1244.98,49.799200,49.799200,49.799200
XS GIS Cut Line= 6
1187680.01148056832941.5592450041187618.81191003832970.605837259
1187565.12588431832994.1567684241187563.28315601 832994.93416949
1187508.85154587833018.5440723751187449.29750477 833049.29000067
#Sta/Elev= 30
9872.633109.81799877.369107.28259888.263102.44669910.05392.152629920.94886.15549
9942.70675.080079950.384 70.85069960.61965.825329967.78463.172829971.36761.46913
9978.53257.310189985.69754.1629610000.02 49.639210003.59 49.753410010.7552.22806
10014.3253.1393510028.6354.3750310035.7855.5393310050.0859.3385710057.2462.42667
10068.2166.2959810079.0371.1368310082.9873.1526510090.3777.6958210094.06 79.6972
10100.4883.0948110105.1485.0464210107.6385.2089610116.2184.7511110127.3585.32322
#Mann= 3 , 0 , 0
9872.633    0.12       09872.633    0.12       010127.35    0.12       0
#XS Ineff= 2 , 0
       0                               0
Bank Sta=9872.633,10127.35
Exp/Cntr=0.3,0.1

Type RM Length L Ch R = 1 ,1195.181,49.799200,49.799200,49.799200
XS GIS Cut Line= 6
1187638.49823734832876.1537614931187570.82509488832923.710682663
1187537.79451116832952.1920418221187517.86549403832970.628882822
1187495.40060691832988.6046063371187435.52524379 833029.34066568
#Sta/Elev= 30
9872.673 103.2829875.283 101.5679879.29399.429999884.16996.234199889.87593.33236
9899.34389.271169906.99385.09295  9912.782.915939924.11277.53524 9941.2370.45614
9972.81855.641389981.48251.921819993.16346.494589994.47846.034029998.81145.65114
10007.8846.8611210027.3148.1928510032.5648.8060810042.4750.9681310046.6752.18103
10059.0456.4926710090.7870.7455210098.7274.0749410102.6976.5095710106.6579.64815
10110.6282.3067710111.7482.8274910118.5685.1481110122.5385.4087610127.3585.33221
#Mann= 3 , 0 , 0
9872.673    0.12       09872.673    0.12       010127.35    0.12       0
#XS Ineff= 2 , 0
       0                               0
Bank Sta=9872.673,10127.35
Exp/Cntr=0.3,0.1

Type RM Length L Ch R = 1 ,1145.381,49.799200,49.799200,49.799200
XS GIS Cut Line= 6
1187595.16718925832835.6316925261187531.55790175832887.188143314
1187511.90767018 832906.10590003 1187469.0757691832953.286504818
1187443.32943355 832976.084796841187406.15410755833005.481416623
#Sta/Elev= 30
9872.66191.501379878.75788.958879891.426 84.40249899.87380.625739908.31977.66777
9921.46170.625379947.51358.128449957.621 53.72069973.00947.556219985.67843.25635
9994.40241.102069997.07940.8179810016.5243.2159710029.9343.4730210034.3943.77236
10040.7745.4359810048.0448.2314510057.9452.5000210063.1254.1666610067.5155.92033
10077.7460.6842210093.1768.4120410098.7471.4522110105.7276.1447110114.0882.17471
10118.2684.51392 10119.985.1644510122.45  85.77510125.1986.1783710127.3386.11622
#Mann= 3 , 0 , 0
9872.661    0.12       09872.661    0.12       010127.33    0.12       0
#XS Ineff= 2 , 0
       0                               0
Bank Sta=9872.661,10127.33
Exp/Cntr=0.3,0.1

Type RM Length L Ch R = 1 ,1095.582,49.799200,49.799200,49.799200
XS GIS Cut Line= 6
1187572.20376057 832807.398263421187494.98720698832868.830960407
1187480.34980183832877.4623888361187456.80007234832887.407632122
1187442.12706482832896.980607855 1187369.7553972832959.906281046
#Sta/Elev= 30
9872.667  85.131 9874.5384.432839883.05580.102789899.68572.292519912.26266.83133
9916.45465.286589924.83961.708079935.75258.054369958.37948.694879970.95743.79831
9974.80142.821829982.41839.616339985.85138.883089989.92138.486629997.02237.04803
10000.5536.96017 10007.737.3147910018.8738.9386610029.4238.5647710039.7536.86881
10043.5837.2492310044.7537.5694810052.2739.8260710065.3244.1706710069.6645.78436
 10091.455.64809 10100.158.9948610109.7664.2420410121.84 73.525910127.3277.41405
#Mann= 3 , 0 , 0
9872.667    0.12       09872.667    0.12       010127.32    0.12       0
#XS Ineff= 2 , 0
       0                               0
Bank Sta=9872.667,10127.32
Exp/Cntr=0.3,0.1

Type RM Length L Ch R = 1 ,1045.783,49.799200,49.799200,49.799200
XS GIS Cut Line= 6
1187526.77768089832756.9373392641187469.21758036832808.566656741
1187451.51996489 832827.804321861187436.07030986832847.296789579
 1187410.1299044832878.4066117651187348.65641362832938.298443014
#Sta/Elev= 30
9872.66564.263349888.52357.804829897.33854.821989903.87552.97613 9910.5651.79406
9918.61549.080869928.18947.121679937.00344.528239955.09440.535539987.66235.28203
9995.41432.95606   1000132.2239310004.4632.2502610008.7332.6760410017.2834.34969
10031.4934.6635410041.5135.5096710046.2936.8547510057.1539.3286910061.8540.82369
10069.1943.7055810075.9645.8160310090.0650.7482610094.7652.5968410099.4754.81623
10105.8357.3283610110.4159.5254510118.2763.9526410122.9767.3495410127.3370.84566
#Mann= 3 , 0 , 0
9872.665    0.12       09872.665    0.12       010127.33    0.12       0
#XS Ineff= 2 , 0
       0                               0
Bank Sta=9872.665,10127.33
Exp/Cntr=0.3,0.1

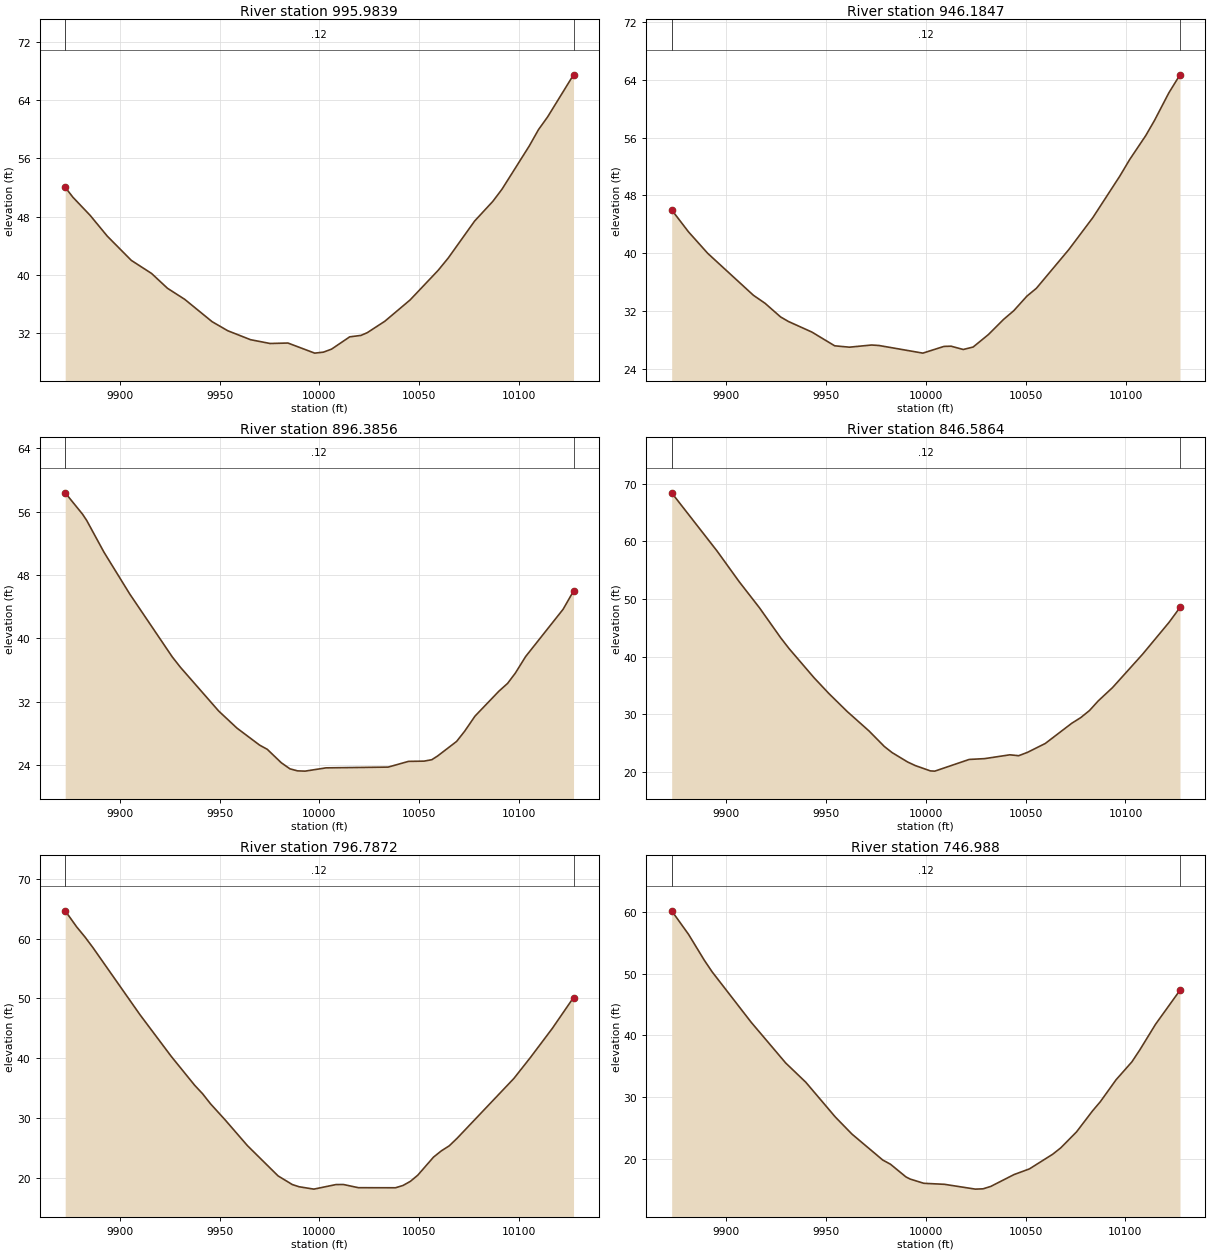
Type RM Length L Ch R = 1 ,995.9839,49.799200,49.799200,49.799200
XS GIS Cut Line= 6
1187491.66645972 832730.057795351187420.96809092832790.257104568
1187398.25736437832814.8504985731187396.98222899832816.391287253
1187364.28769191832852.9212884721187308.79246997 832906.77125658
#Sta/Elev= 30
9872.66952.028819876.53150.661889885.14948.181019893.76845.319479905.78941.99887
 9915.9140.210459923.93138.167229932.54936.653219946.27433.586759954.09532.34668
9965.52431.115719975.33130.594139984.26230.65748 9997.6629.2722710002.0129.40533
 10006.129.8170310015.2231.5082110020.8631.7029510024.0332.0806810032.83 33.6512
10045.4636.5681510059.49  40.62110064.61 42.333410077.7847.3910610086.9250.09964
10091.4951.7562410105.2157.7142710109.7859.9359610114.3561.6789510127.3567.46087
#Mann= 3 , 0 , 0
9872.669    0.12       09872.669    0.12       010127.35    0.12       0
#XS Ineff= 2 , 0
       0                               0
Bank Sta=9872.669,10127.35
Exp/Cntr=0.3,0.1

Type RM Length L Ch R = 1 ,946.1847,49.799100,49.799100,49.799100
XS GIS Cut Line= 6
1187470.29591346832713.6099145991187409.08516129832757.314461849
1187345.34234139832787.8482936791187321.01702196832802.266491164
1187292.72428922832823.7292899651187259.42532649832853.684861308
#Sta/Elev= 30
9872.66646.006949881.10842.967619890.73340.003019913.61934.211799919.43133.11002
9927.22831.222669931.15230.594539942.92329.130259954.31127.235819961.71527.04555
9972.82227.344889976.52427.277959998.47726.2246810009.0627.1506810012.6327.18133
10018.7226.7272910023.6727.06417 10031.3 28.781810038.9230.8801810044.01 32.0765
10050.63 34.099510055.3435.1701510071.6240.5285910083.6644.94701 10097.250.69207
 10102.152.9603910110.1356.2600710114.5558.3702510121.73 62.1739 10127.364.65657
#Mann= 3 , 0 , 0
9872.666    0.12       09872.666    0.12       0 10127.3    0.12       0
#XS Ineff= 2 , 0
       0                               0
Bank Sta=9872.666,10127.3
Exp/Cntr=0.3,0.1

Type RM Length L Ch R = 1 ,896.3856,49.799200,49.799200,49.799200
XS GIS Cut Line= 6
1187460.87042852832657.3337110111187395.32590707832709.808032725
1187355.21783259832733.5595542621187326.70085561832746.080762803
 1187305.8250971832759.4031473281187254.73497112832804.331287915
#Sta/Elev= 30
9872.67358.394799881.36155.693419883.46254.89491 9892.0650.904749904.956 45.6256
9926.31937.651299930.38536.344029949.55930.814719958.70328.657019970.08926.49988
9973.88525.977249980.94124.271659985.27123.506179989.06623.251139992.86123.21855
10003.32 23.631810034.4623.7271310044.64 24.451310052.4324.4816310056.3224.66156
10059.2325.1333710068.75 26.974510072.7628.2593210077.9730.1763910089.8833.31011
 10094.3 34.312810098.1635.6079310103.3237.7023210122.0843.6727210127.3145.97792
#Mann= 3 , 0 , 0
9872.673    0.12       09872.673    0.12       010127.31    0.12       0
#XS Ineff= 2 , 0
       0                               0
Bank Sta=9872.673,10127.31
Exp/Cntr=0.3,0.1

Type RM Length L Ch R = 1 ,846.5864,49.799200,49.799200,49.799200
XS GIS Cut Line= 6
1187394.50633679832597.0178883081187345.94046184832658.864813792
1187320.97153324832699.4851420131187320.00024743832701.233456594
 1187302.0698027 832729.483086351187239.65002502832798.217234066
#Sta/Elev= 30
9872.68368.395789895.42958.303789906.45253.014159916.67848.461229927.30343.26543
9931.48141.397869943.99636.344719951.31933.646359960.58530.494939971.51627.12482
9979.21824.423589983.069 23.37399990.77121.759079994.62221.1304610002.28 20.1928
 10004.520.1547510021.7122.1793810029.4922.3225910042.0822.9828510046.5122.82807
10050.9523.4135710059.8124.94522 10073.128.4531610077.5429.4193410081.97 30.6571
 10086.432.3425110093.5434.6446810108.5640.4159210121.8545.9544910127.3148.52284
#Mann= 3 , 0 , 0
9872.683    0.12       09872.683    0.12       010127.31    0.12       0
#XS Ineff= 2 , 0
       0                               0
Bank Sta=9872.683,10127.31
Exp/Cntr=0.3,0.1

Type RM Length L Ch R = 1 ,796.7872,49.799200,49.799200,49.799200
XS GIS Cut Line= 6
 1187340.9831997832569.3467238321187301.02534486832630.077638733
1187275.33947217832679.4213604941187252.17067611 832722.61338266
1187235.50122419832747.4737913691187206.65795361832785.078134901
#Sta/Elev= 30
9872.673 64.63749878.45261.937169882.60860.254319886.535 58.50229910.09947.29208
9925.80840.30664 9937.5935.460019941.51734.06097 9945.4432.399639952.84129.68273
9963.94225.403049979.33720.33323 9986.4318.895799989.84618.523769997.24718.12762
10008.3718.8931910012.0918.8985110019.5418.3673210038.1518.3551610041.8718.73308
 10045.619.4265610049.3120.4583410057.18 23.470810061.13 24.526810065.0825.36632
10069.0326.6318110097.4636.6235110105.7340.1211910116.6944.9795810127.3450.14578
#Mann= 3 , 0 , 0
9872.673    0.12       09872.673    0.12       010127.34    0.12       0
#XS Ineff= 2 , 0
       0                               0
Bank Sta=9872.673,10127.34
Exp/Cntr=0.3,0.1

Type RM Length L Ch R = 1 , 746.988,49.799200,49.799200,49.799200
XS GIS Cut Line= 6
1187300.35706547832547.6138647011187270.08600768832593.423132172
1187232.46918478832654.1816979121187231.40918695832655.877694552
1187199.92645582832706.1704912831187162.25582123832761.614883226
#Sta/Elev= 30
9872.632 60.16279881.10156.346589888.966 52.17389892.89950.287469912.56142.08236
9929.774 35.52239939.85332.402639954.70426.752589963.00524.00122 9978.4419.79985
9982.29919.125329990.01617.07796  9992.116.73103    999916.0377710009.3415.87474
10024.8215.0957610028.6915.1457610032.5615.5372610044.1817.4512610051.9218.37254
10063.6120.7539910067.5821.7679210075.5124.3608610083.5327.7611810087.41 29.2367
10095.3432.8073910103.2735.7078810107.2437.6473310115.1741.8164810127.3747.30337
#Mann= 3 , 0 , 0
9872.632    0.12       09872.632    0.12       010127.37    0.12       0
#XS Ineff= 2 , 0
       0                               0
Bank Sta=9872.632,10127.37
Exp/Cntr=0.3,0.1

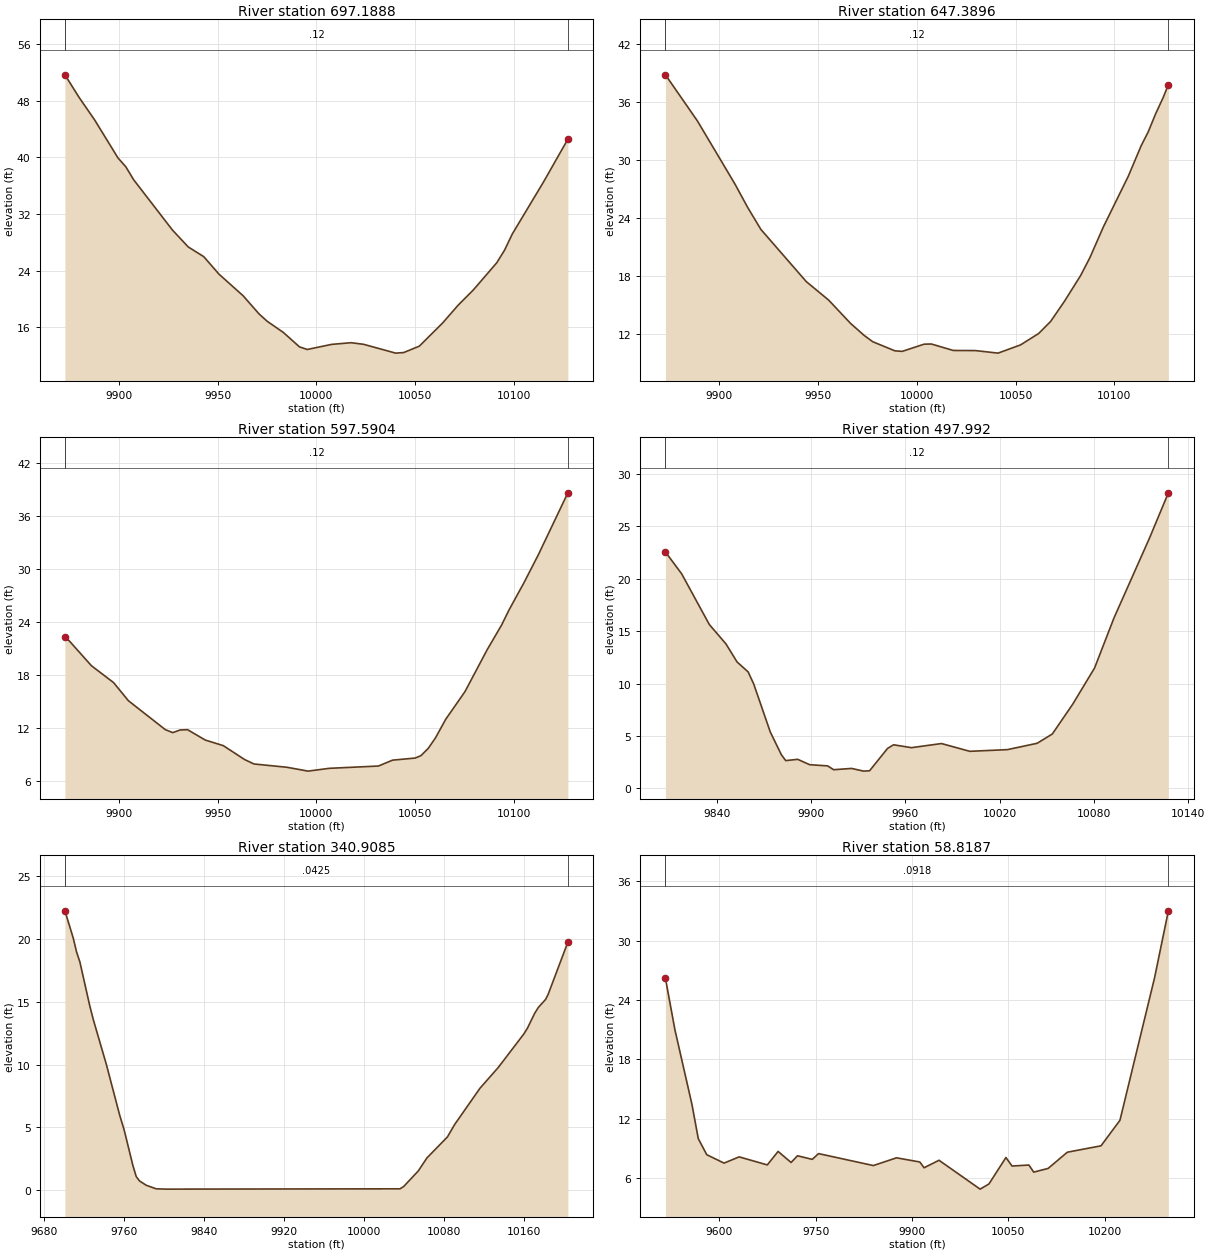
Type RM Length L Ch R = 1 ,697.1888,49.799200,49.799200,49.799200
XS GIS Cut Line= 6
1187263.13838883 832522.493271071187215.35836079832593.810461808
1187191.28701123832626.4106478311187190.08701128832628.010647867
1187163.85435908832664.0488437311187118.95610229 832732.41513206
#Sta/Elev= 30
9872.63351.651229879.783 48.46999887.68145.278359899.52839.899549903.47738.65839
9907.42636.835249927.10329.71847 9935.0727.340779942.96825.959169950.68123.48558
9962.85220.450739971.00917.858149975.08716.834869983.24315.26165  9991.4 13.2262
9995.35812.8506210007.6913.5690510017.5813.8080410023.9213.5805510040.1512.33544
10044.2112.4167510052.1113.3150710063.8816.5750710071.73 19.086510079.5821.28676
10091.3625.1000610095.2826.8663710099.2429.1698210114.9136.4487210127.3742.55572
#Mann= 3 , 0 , 0
9872.633    0.12       09872.633    0.12       010127.37    0.12       0
#XS Ineff= 2 , 0
       0                               0
Bank Sta=9872.633,10127.37
Exp/Cntr=0.3,0.1

Type RM Length L Ch R = 1 ,647.3896,49.799200,49.799200,49.799200
XS GIS Cut Line= 6
1187214.95030457832487.0652695331187174.97029401 832553.25571446
 1187151.7878301 832596.450945091187150.93381754832598.259442409
1187140.38776826832618.5532129291187088.05753774832707.839785679
#Sta/Elev= 30
9872.64938.797469888.85134.017129907.88827.473029914.23325.086019920.97822.78858
9943.97517.380989955.31715.46417  9966.413.054129973.338 11.79979977.65811.15333
9988.82810.214159992.55210.1551110003.6510.9017710007.3510.9179310018.4410.24999
10029.6910.23757 10041.19.97436310052.5110.8281910061.6712.0079110067.7213.25303
10074.65 15.316510082.9318.0143510087.6319.8707210094.3423.0008410107.0928.30761
10113.5831.4528410117.1632.8922510120.9634.7846310124.7636.4593110127.3637.78862
#Mann= 3 , 0 , 0
9872.649    0.12       09872.649    0.12       010127.36    0.12       0
#XS Ineff= 2 , 0
       0                               0
Bank Sta=9872.649,10127.36
Exp/Cntr=0.3,0.1

Type RM Length L Ch R = 1 ,597.5904,99.598400,99.598400,99.598400
XS GIS Cut Line= 6
1187161.77990721832464.2102836291187129.45217408832522.916696024
1187105.77484763832577.2965533091187105.06706349832579.167125846
1187085.89024086832624.2843200281187049.54200816832692.521328569
#Sta/Elev= 30
 9872.6722.229819874.82521.846399886.06119.027249897.29717.112549904.78815.06523
9923.51511.78387 9927.2611.446829931.00511.748289934.75111.783759943.74310.60718
9952.8639.9758099963.5988.4071599968.3987.8990489985.0687.5273229995.8037.089745
10006.487.40574810031.437.66769110038.568.33229610050.02 8.5690210052.94 8.84217
10056.669.66993610060.3710.8728110065.4812.9553410075.2416.0870710086.4220.80968
10093.8323.6451310097.5525.3360710104.9828.3606410112.4231.5942910127.3438.59548
#Mann= 3 , 0 , 0
 9872.67    0.12       0 9872.67    0.12       010127.34    0.12       0
#XS Ineff= 2 , 0
       0                               0
Bank Sta=9872.67,10127.34
Exp/Cntr=0.3,0.1

Type RM Length L Ch R = 1 , 497.992,157.083500,157.083500,157.083500
XS GIS Cut Line= 6
1187147.28603297832405.379747346  1187076.028557 832433.29206194
1187017.46711001832532.3718945241187016.43150473832534.082894713
1187000.82104421832560.2242232561186953.99426365832643.940370321
#Sta/Elev= 30
9807.378 22.54019817.69920.457769835.31715.621119845.88713.778259852.935 12.0604
9859.98211.111849863.5059.9711659874.0765.3843899881.1233.2171989883.9082.655859
9891.5262.7772949899.1482.2642679910.5822.1528499914.3931.7877829925.8261.910023
9933.4481.6527489937.2591.6873669948.6923.8158919952.5034.1626969963.9363.889491
9982.9924.281541   100013.54089210024.993.70234410043.894.30724110053.535.191803
10066.45 8.0199610080.4211.4853810092.7616.2516310115.3223.8519310127.3728.18013
#Mann= 3 , 0 , 0
9807.378    0.12       09807.378    0.12       010127.37    0.12       0
#XS Ineff= 2 , 0
       09939.208                       0
Bank Sta=9807.378,10127.37
Exp/Cntr=0.3,0.1

Type RM Length L Ch R = 1 ,340.9085,282.089800,282.089800,282.089800
XS GIS Cut Line= 6
1187142.62818068832378.7634484921186900.74250808832414.214775458
1186874.41751477832467.3844453251186873.56020838832469.191383541
1186845.22135475832527.6131718461186787.96599868832646.922659278
#Sta/Elev= 30
9701.15622.224099709.47620.055589712.79218.955749716.10818.156279726.05614.65472
9729.37213.620639742.63510.000279755.8995.984804 9760.424.7960829769.1621.968879
9772.4781.0958529775.7940.7482839782.4260.4078729792.3740.1243989802.3210.098364
10036.330.12236410039.980.30516510054.571.53994510063.312.58265310083.714.243561
10090.995.23607810116.32 8.1195510134.669.77433110160.13 12.428310163.7712.88986
10171.0514.0779410174.6914.5417210181.9715.1817410184.5715.5952210204.2219.73397
#Mann= 3 , 0 , 0
9701.156  0.0425       09701.156  0.0425       010204.22  0.0425       0
#XS Ineff= 2 , 0
       09949.698                       0
Bank Sta=9701.156,10204.22
Exp/Cntr=0.3,0.1

Type RM Length L Ch R = 1 , 58.8187,30.559400,30.559400,30.559400
XS GIS Cut Line= 6
1187181.88722149832290.2642548681187116.01188186832298.249144524
 1186984.2612026832328.8578881771186803.93577799832324.865443364
1186750.03777286832316.2151462291186457.25848565832131.231869325
#Sta/Elev= 30
9515.902 26.18459530.69320.984519557.13213.476269567.04610.006629580.2668.384921
9607.1737.536622 9630.758.1670239674.537 7.354229691.3788.7159179711.587 7.60095
9721.5858.2767169744.5567.9155879754.4018.4962499839.7247.2907289875.8228.071947
9912.0967.6490239918.7427.0671279942.0017.82318110006.014.910404 10019.85.431428
10046.248.10228910055.767.241173   100827.34327410089.496.62787310111.967.000058
10141.92 8.6380310194.359.28217310223.8411.8602210277.7426.2443110299.25 33.0042
#Mann= 3 , 0 , 0
9515.902  0.0918       09515.902  0.0918       010299.25  0.0918       0
#XS Ineff= 2 , 0
       0  9959.9        10039.46       0
Bank Sta=9515.902,10299.25
Exp/Cntr=0.3,0.1

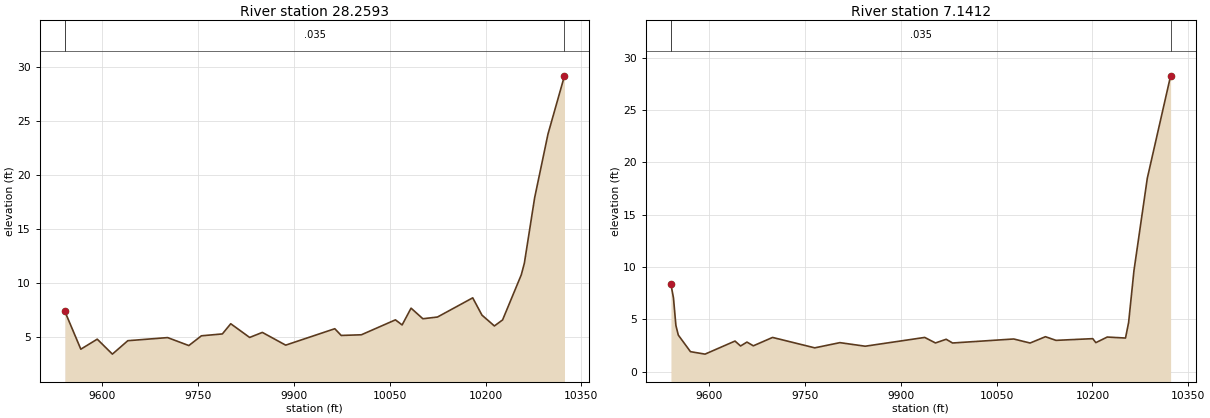
Type RM Length L Ch R = 1 , 28.2593,21.118100,21.118100,21.118100
XS GIS Cut Line= 6
1187165.91744218832233.7046198431187080.74528588832283.610180143
1186998.90016697832299.5799594551186738.72584579832268.305808339
1186610.30220393832209.749950889 1186461.2509305832082.657123941
#Sta/Elev= 30
9541.0267.4282029566.1533.9057979591.8634.8346269615.5863.4485529639.7424.692386
9702.0754.9798069735.2774.2422529754.968 5.145159787.7885.3191899800.9166.262994
9830.5084.9933679850.427 5.459479886.9444.2806079963.8445.8023439973.9025.178273
10005.47 5.2403110058.79 6.6233910069.286.15227210083.287.70752610101.77  6.7257
10124.656.88458410179.838.66196110194.287.06217710213.766.05805410226.616.618155
10255.8810.79582 10260.711.8734710276.7917.93195 10297.723.8354210323.5229.22643
#Mann= 3 , 0 , 0
9541.026   0.035       09541.026   0.035       010323.52   0.035       0
#XS Ineff= 2 , 0
       09961.566           10037       0
Bank Sta=9541.026,10323.52
Exp/Cntr=0.3,0.1

Type RM Length L Ch R = 1 ,  7.1412,0.000000,0.000000,0.000000
XS GIS Cut Line= 6
1187177.22936919832215.7386181281187092.05721288832265.644178428
1187010.21209397832281.613957741 1186750.0377728832250.339806624
1186621.61413094832191.783949174 1186472.5628575832064.691122227
#Sta/Elev= 30
9539.957 8.350859543.9727.0560429547.7754.4170269551.5773.488772 9570.591.905439
9593.4051.6700219640.3572.920512 9649.022.4489419659.0482.8210249669.0762.465911
9699.1613.2669169765.2162.2713389804.5992.7684619844.2062.4268549937.4553.267585
9954.2192.7377329970.9823.0908939981.0412.73485610076.783.11785310102.412.731731
10126.423.33590610143.012.98651410200.553.15008510205.372.76815210223.233.304041
10251.823.20849410256.694.69457710265.059.65161110285.96 18.494110322.4528.28745
#Mann= 3 , 0 , 0
9539.957   0.035       09539.957   0.035       010322.45   0.035       0
#XS Ineff= 2 , 0
       09962.941        10034.74       0
Bank Sta=9539.957,10322.45
Exp/Cntr=0.3,0.1